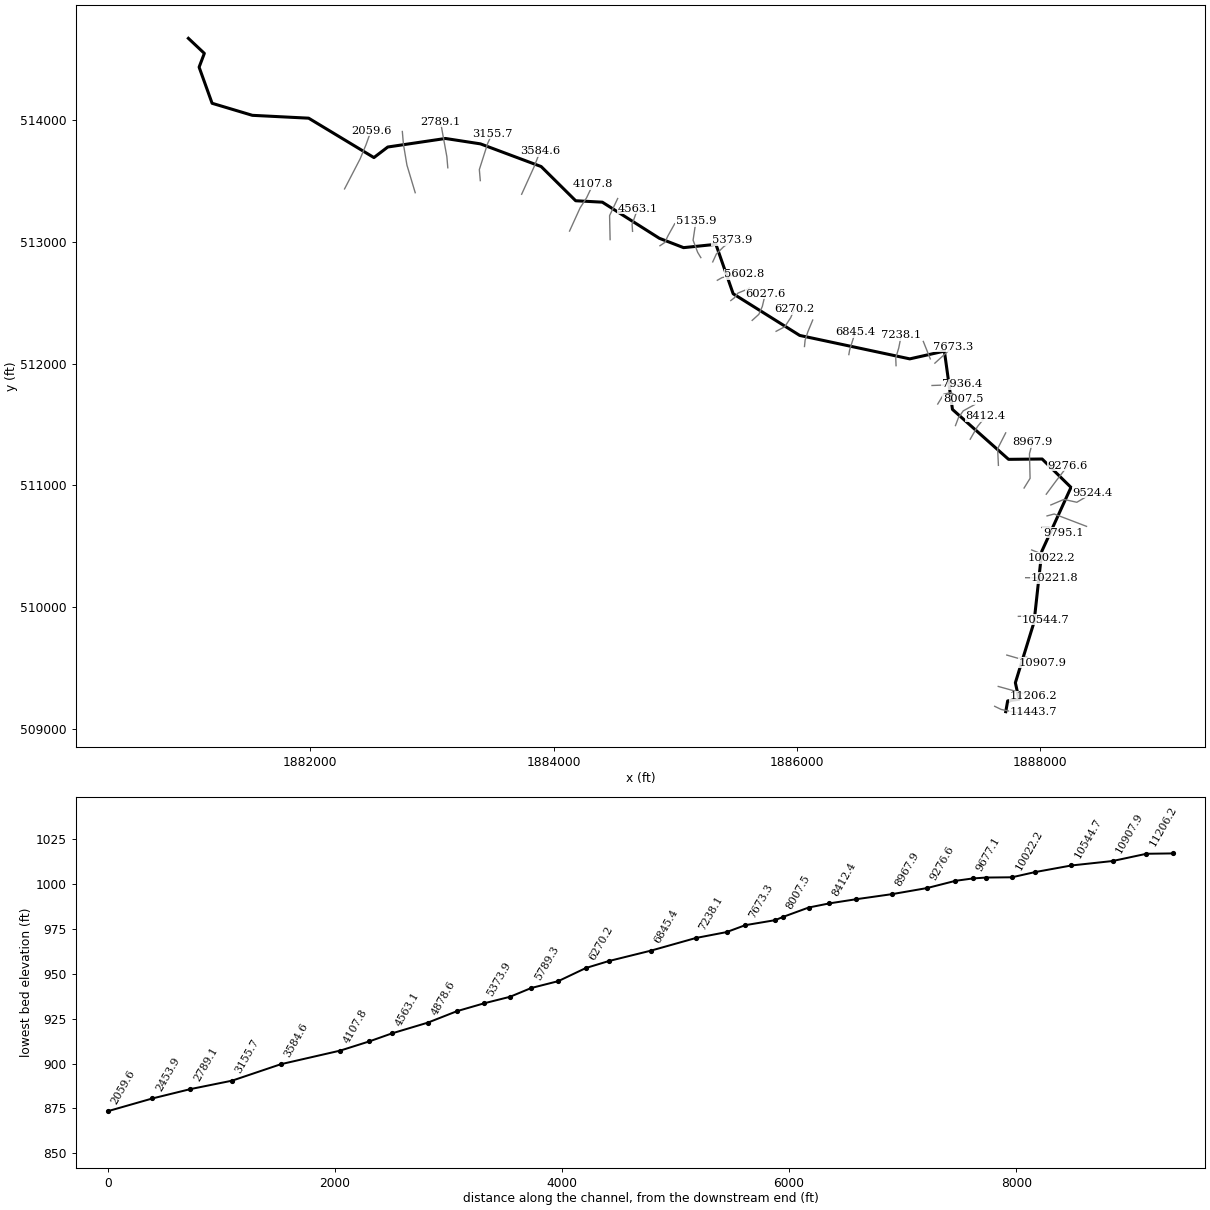
--- HORSEFRK.prj (project) ---

Proj Title=HORSEFRK
Current Plan=p01
Default Exp/Contr=0,0
English Units
Geom File=g01
Flow File=f01
Plan File=p01
BEGIN DESCRIPTION:
END DESCRIPTION:
DSS Export Rating Curves= 0
DSS Export Rating Curve Sorted= 0
DSS Export Volume Flow Curves= 0
DXF OffsetX= 0
DXF OffsetY= 0
DXF ScaleX= 0
DXF ScaleY= 0

--- HORSEFRK.p01 (plan) ---

Plan Title=Floodplain
Program Version=4.00
Geom File=g01
Flow File=f01
K Sum by GR=0
Std Step Tol=0.01
Critical Tol=0.01
Num of Std Step Trials=20
Max Error Tol=0.3
Flow Tol Ratio=0.001
Split Flow NTrial=30
Split Flow Tol=0.02
Split Flow Ratio=0.02
Log Output Level=0
Friction Slope Method=1
Unsteady Friction Slope Method=2
Unsteady Bridges Friction Slope Method=1
Global Log Level=0
CheckData=False
Run HTab=0
Run UNet=0
Run PostProcess=0
UNET Theta=0
UNET Theta Warmup=0
UNET ZTol=0
UNET ZSATol=0
UNET MxIter=0
UNET MaxInSteps=0
UNET DtIC=0
UNET DtMin=0
UNET MaxCRTS=0
UNET WFStab=0
UNET SFStab=0
UNET WFX=0
UNET SFX=0
UNET DSS MLevel=0
UNET DZMax Abort=0
UNET Convert EG Bridges=0
UNET Use Existing IB Tables=0
UNET Froude Limit=0
UNET Froude Power=0
Write IC File=0
Echo Input=False
Echo Output=False
Write Detailed=0

--- HORSEFRK.f01 (steady flow) ---

Flow Title=NFF Regression Equation
Program Version=4.10
Number of Profiles= 1
Profile Names=P100yr
River Rch & RM=HORSEFRK,Main            ,11443.7
804.9984
River Rch & RM=HORSEFRK,Main            ,10907.9
895.5905
River Rch & RM=HORSEFRK,Main            ,9276.6
967.2148
River Rch & RM=HORSEFRK,Main            ,7509.2
1063.719
River Rch & RM=HORSEFRK,Main            ,5789.3
1152.673
River Rch & RM=HORSEFRK,Main            ,2059.6
1327.048
River Rch & RM=HORSEFRK,Main            ,541.3
1357.229
Boundary for River Rch & Prof#=HORSEFRK,Main            , 1
Up Type= 0
Dn Type= 3
Dn Slope=0.01
DSS Import GetInterval= 0
DSS Import GetPeak= 0
DSS Import FillOption= 0

--- HORSEFRK.g01 (geometry) ---

Geom Title=USGS 10m DEM
Program Version=4.10

River Reach=HORSEFRK        ,Main
Reach XY= 30
     1887715.846      509138.767     1887731.471      509227.308
     1887824.765      509241.168     1887794.817      509376.585
     1887948.463      509875.283     1888012.265      510457.314
     1888251.848      510982.054     1888014.869      511215.127
     1887738.827      511212.522      1887277.89      511622.679
     1887211.484      512101.845     1886927.065      512038.114
     1886022.682      512230.752     1885475.807      512573.199
      1885333.88      512979.449     1885068.255      512952.106
     1884868.654      513029.284     1884400.834      513325.762
     1884181.536      513337.522     1883898.095      513618.494
     1883398.984       513804.97     1883111.223      513849.241
     1882637.352      513779.102     1882523.636      513692.297
     1881987.178      514016.081     1881524.505      514039.519
     1881193.775      514138.477     1881087.005      514435.352
     1881129.973      514548.634     1880998.945      514672.191

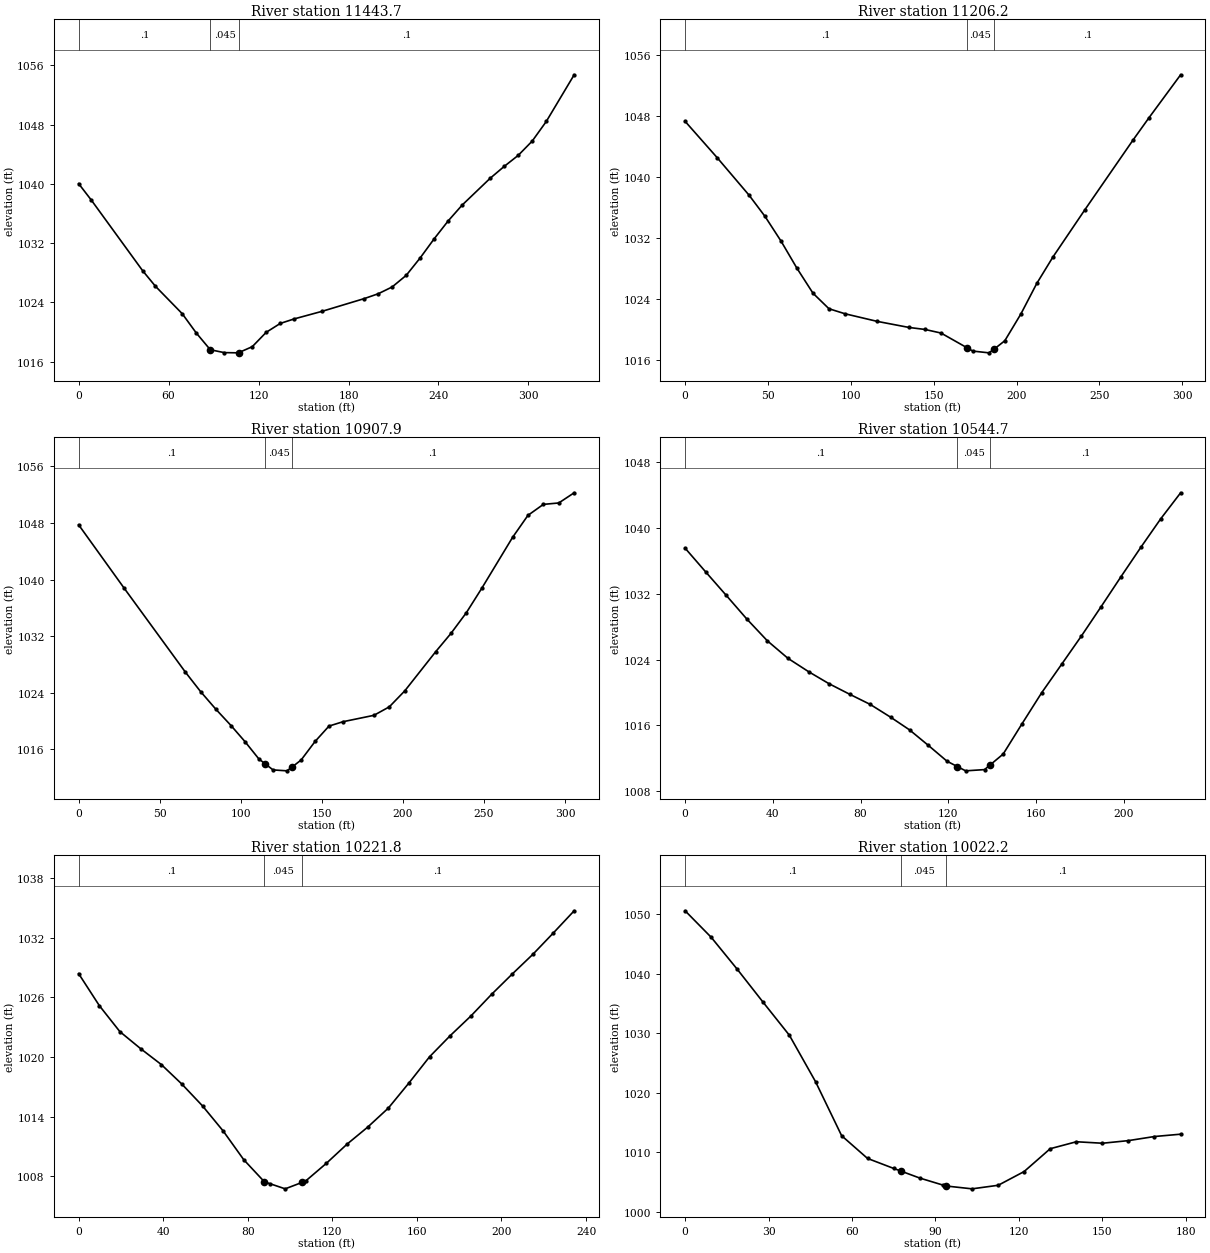
Type RM Length L Ch R = 1 ,11443.7 ,241.6,237.5,233.2
XS GIS Cut Line= 4
       1887624.7      509183.037     1887678.519      509156.996
     1887833.901      509124.878     1887945.012      509139.635
#Sta/Elev= 29
       0 1040.03     8.5  1037.8    42.7 1028.28    51.2 1026.19    69.1 1022.48
    78.5 1019.87    87.8 1017.62    97.1 1017.23   106.5  1017.2   106.9 1017.24
   115.8 1018.03   125.1 1019.97   134.5 1021.17   143.8 1021.78   162.5 1022.81
   190.5 1024.52   199.8 1025.17   209.1 1026.09   218.5 1027.66   227.8 1030.01
   237.1 1032.58   246.5 1035.01   255.8 1037.14   274.5 1040.76   283.8 1042.35
   293.2 1043.85   302.5 1045.77   311.9 1048.42   330.5 1054.72
#Mann= 3 , 0 , 0
       0      .1       0    87.8    .045       0   106.9      .1       0
Bank Sta=87.8,106.9
XS Rating Curve= 0 ,0
Exp/Cntr=0.3,0.1

Type RM Length L Ch R = 1 ,11206.2 ,285.5,298.4,309.6
XS GIS Cut Line= 2
     1887654.214      509346.232     1887942.408      509266.371
#Sta/Elev= 25
       0 1047.28    19.3 1042.54    38.6 1037.62    48.2 1034.85    57.9 1031.61
    67.5 1028.06    77.2 1024.79    86.8 1022.77    96.5 1022.11   115.8 1021.12
   135.1 1020.32   144.7 1020.06   154.4 1019.59   169.9 1017.69   173.6 1017.23
   183.3    1017  186.54  1017.5   192.9 1018.58   202.6 1022.08   212.2 1026.08
   221.9 1029.52   241.2 1035.71   270.1 1044.78   279.8 1047.72     299 1053.37
#Mann= 3 , 0 , 0
       0      .1       0   169.9    .045       0  186.54      .1       0
Bank Sta=169.9,186.54
XS Rating Curve= 0 ,0
Exp/Cntr=0.3,0.1

Type RM Length L Ch R = 1 ,10907.9 ,369.9,363.1,355.9
XS GIS Cut Line= 4
     1887724.526      509604.044     1887814.804      509578.003
      1887883.38      509586.683     1888017.929      509539.808
#Sta/Elev= 28
       0 1047.74    28.2 1038.74    65.8 1026.92    75.2 1024.16    84.6 1021.67
      94 1019.35   102.6 1017.08   111.2 1014.62   114.9 1013.97   119.9 1013.08
   128.5 1012.95  131.75 1013.51   137.2 1014.48   145.8  1017.1   154.4 1019.28
   163.1  1019.9   182.1  1020.8   191.6    1022   201.1 1024.25   220.1 1029.77
   229.6 1032.38   239.1 1035.31   248.6 1038.76   267.6 1045.96   277.1 1049.08
   286.6 1050.63   296.1 1050.83   305.6 1052.27
#Mann= 3 , 0 , 0
       0      .1       0   114.9    .045       0  131.75      .1       0
Bank Sta=114.9,131.75
XS Rating Curve= 0 ,0
Exp/Cntr=0.3,0.1

Type RM Length L Ch R = 1 ,10544.7 ,318.7,323,327.2
XS GIS Cut Line= 4
     1887819.578      509922.187     1887913.328      509924.791
     1887971.922      509913.072     1888042.235      509896.145
#Sta/Elev= 28
       0 1037.53     9.4 1034.64    18.8 1031.78    28.1 1028.93    37.5 1026.27
    46.9 1024.14    56.3 1022.52    65.6 1021.06      75 1019.78    84.4 1018.54
    93.8 1016.97   102.3 1015.45   110.9 1013.56   119.4 1011.64   124.1 1010.99
   127.9 1010.47   136.5 1010.62   139.1  1011.2     145 1012.51   153.5 1016.15
   162.6 1019.98   171.6  1023.4   180.7 1026.87   189.7 1030.44   198.7 1034.06
   207.8 1037.65   216.8 1041.09   225.9 1044.26
#Mann= 3 , 0 , 0
       0      .1       0   124.1    .045       0   139.1      .1       0
Bank Sta=124.1,139.1
XS Rating Curve= 0 ,0
Exp/Cntr=0.3,0.1

Type RM Length L Ch R = 1 ,10221.8 ,207.8,199.6,190.9
XS GIS Cut Line= 2
     1887879.474      510239.895     1888113.849      510237.291
#Sta/Elev= 27
       0 1028.38     9.8 1025.16    19.5 1022.55    29.3 1020.84    39.1 1019.24
    48.8 1017.28    58.6 1015.08    68.4 1012.55    78.1 1009.67    87.9 1007.44
    90.6 1007.25    97.7 1006.74   105.6 1007.38   107.4 1007.53   117.2 1009.31
     127 1011.24   136.7 1012.94   146.5 1014.86   156.3  1017.4     166 1020.02
   175.8 1022.15   185.6 1024.13   195.3 1026.29   205.1 1028.34   214.9 1030.33
   224.6 1032.48   234.4  1034.7
#Mann= 3 , 0 , 0
       0      .1       0    87.9    .045       0   105.6      .1       0
Bank Sta=87.9,105.6
XS Rating Curve= 0 ,0
Exp/Cntr=0.3,0.1

Type RM Length L Ch R = 1 ,10022.2 ,226.6,227.1,228
XS GIS Cut Line= 2
     1887928.953       510467.76     1888094.318      510401.353
#Sta/Elev= 22
       0  1050.6     9.4 1046.14    18.8 1040.75    28.1 1035.21    37.5 1029.69
    46.9  1021.9    56.3 1012.81    65.6    1009      75 1007.32    77.8 1006.84
    84.4  1005.7    92.8 1004.51    93.8 1004.37   103.2 1003.89   112.6 1004.49
   121.9 1006.79   131.3 1010.63   140.7  1011.8   150.1 1011.55   159.4 1011.99
   168.8 1012.68   178.2 1013.07
#Mann= 3 , 0 , 0
       0      .1       0    77.8    .045       0    93.8      .1       0
Bank Sta=77.8,93.8
XS Rating Curve= 0 ,0
Exp/Cntr=0.3,0.1

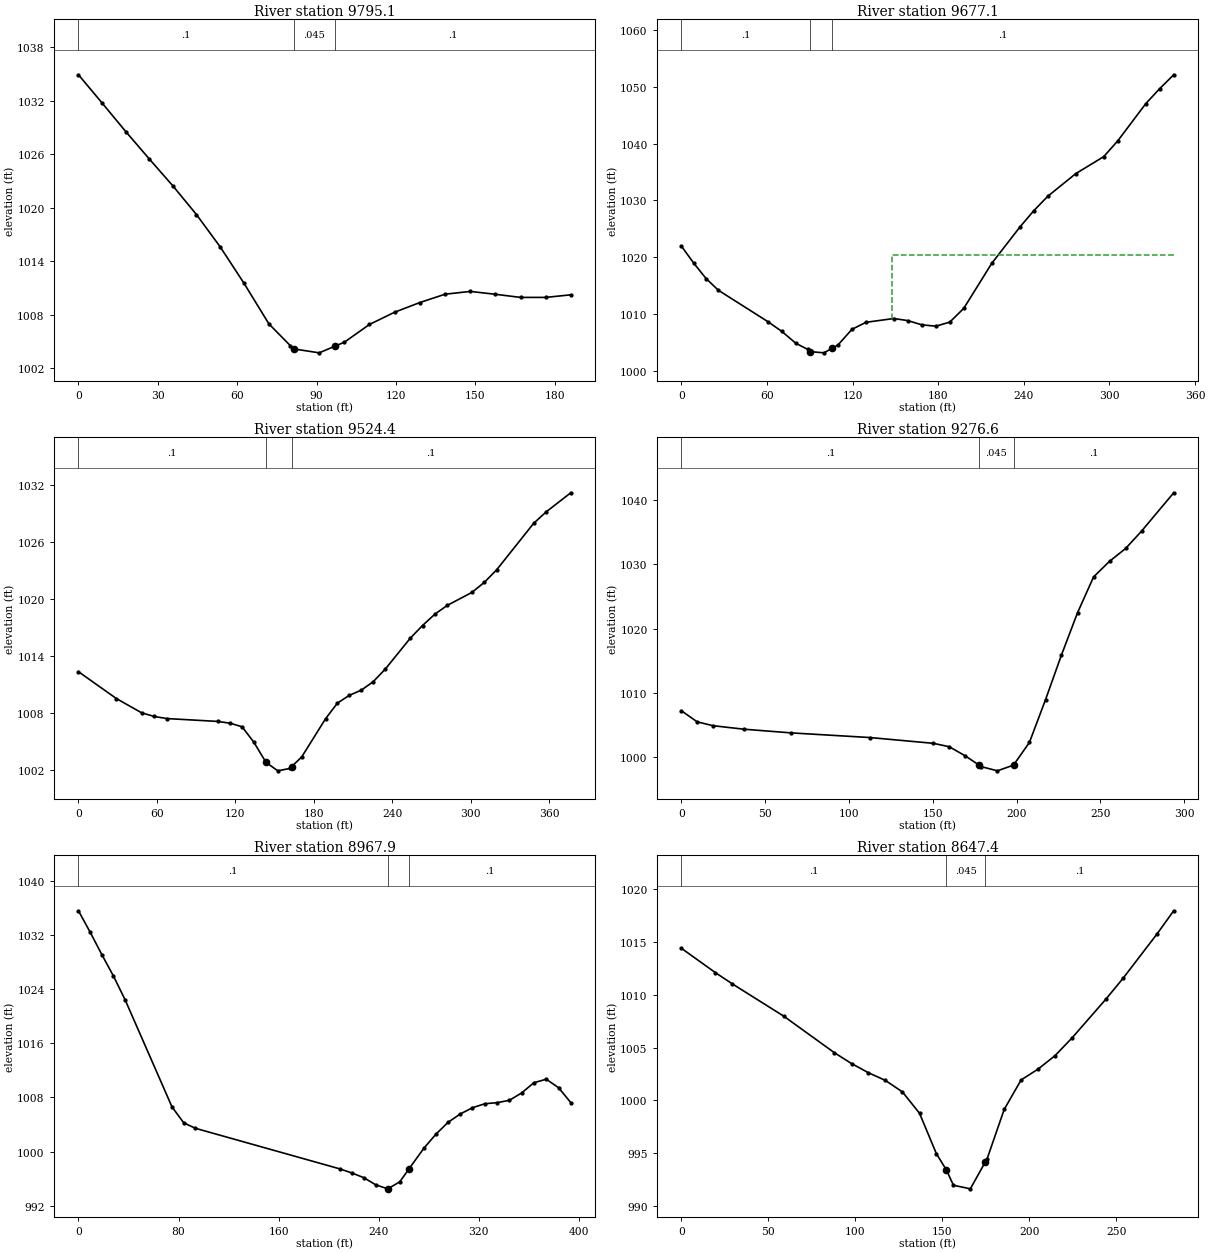
Type RM Length L Ch R = 1 ,9795.1  ,118.1,117.9,117.7
XS GIS Cut Line= 3
     1888010.985      510652.656     1888073.485      510652.656
      1888189.37      510609.687
#Sta/Elev= 24
       0 1034.89     8.9 1031.74    17.9 1028.52    26.8 1025.45    35.7 1022.44
    44.6 1019.23    53.6  1015.6    62.5 1011.57      72 1006.98   80.07 1004.55
    81.5 1004.17    81.8 1004.16      91 1003.74    96.8 1004.47   100.5 1004.93
     110 1006.92   119.5 1008.29     129 1009.37   138.6 1010.31   148.1 1010.62
   157.6  1010.3   167.1 1009.95   176.6 1009.95   186.1 1010.24
#Mann= 3 , 0 , 0
       0      .1       0    81.5    .045       0    96.8      .1       0
Bank Sta=81.5,96.8
XS Rating Curve= 0 ,0
Exp/Cntr=0.3,0.1

Type RM Length L Ch R = 1 ,9677.1  ,149,152.7,156.3
XS GIS Cut Line= 3
     1888055.255      510747.708     1888113.849      510763.333
     1888379.474       510661.77
#Sta/Elev= 30
       0 1021.99     8.7 1018.98    17.3 1016.29      26 1014.22    60.6 1008.72
    70.4    1007    80.2 1004.92   88.66 1003.83    90.1 1003.46    99.9 1003.24
   105.7 1004.05   109.7 1004.61   119.5 1007.36   129.3  1008.6   148.9 1009.27
   158.7  1008.9   168.5 1008.16   178.3 1007.92   188.1 1008.64   197.9 1011.06
   217.5 1018.96   237.2 1025.33     247 1028.22   256.8 1030.75   276.4 1034.72
     296 1037.71   305.8 1040.47   325.4    1047   335.2 1049.65     345 1052.08
#Mann= 3 , 0 , 0
       0      .1       0    90.1    .045       0   105.7      .1       0
#XS Ineff= 2 , 0
                          147.25         1020.43
Permanent Ineff=
       F       F
Bank Sta=90.1,105.7
XS Rating Curve= 0 ,0
Exp/Cntr=0.3,0.1

Type RM Length L Ch R = 1 ,9524.4  ,222.4,247.8,273.2
XS GIS Cut Line= 4
     1888086.505      510837.551     1888193.276      510883.124
     1888300.047      510859.687     1888430.255       510936.51
#Sta/Elev= 30
       0 1012.36      29 1009.53    48.4 1008.02      58 1007.64    67.7 1007.42
   106.4 1007.12   116.1 1006.93   125.2 1006.55   134.3  1004.9   143.4 1002.81
   152.5 1001.91   161.6 1002.16     163 1002.35   170.8 1003.38     189  1007.4
   198.1 1009.05   207.2 1009.87   216.3 1010.41   225.4  1011.3   234.8 1012.65
   253.8 1015.89   263.2 1017.23   272.6 1018.42   282.1 1019.35     301 1020.72
   310.4 1021.77   319.9  1023.1   348.2    1028   357.7  1029.2   376.6 1031.22
#Mann= 3 , 0 , 0
       0      .1       0   143.4    .045       0     163      .1       0
Bank Sta=143.4,163
XS Rating Curve= 0 ,0
Exp/Cntr=0.3,0.1

Type RM Length L Ch R = 1 ,9276.6  ,292.9,308.6,324.1
XS GIS Cut Line= 3
     1888048.745      510926.093      1888126.87      511031.562
     1888225.828      511160.468
#Sta/Elev= 22
       0 1007.24     9.4 1005.52    18.8 1004.92    37.5 1004.37    65.6  1003.8
   112.5 1003.08   150.4 1002.18   159.9 1001.65   169.5 1000.22   177.8  998.77
     179  998.56   188.6  997.91   198.2   998.8   207.7 1002.32   217.3 1008.95
   226.8 1015.88   236.4 1022.45     246 1028.02   255.5 1030.44   265.1 1032.43
   274.6 1035.12   293.8 1041.08
#Mann= 3 , 0 , 0
       0      .1       0   177.8    .045       0   198.2      .1       0
Bank Sta=177.8,198.2
XS Rating Curve= 0 ,0
Exp/Cntr=0.3,0.1

Type RM Length L Ch R = 1 ,8967.9  ,332.1,320.6,308.9
XS GIS Cut Line= 4
     1887866.453      510976.874     1887915.769       511056.33
     1887910.724      511258.124     1887935.464      511353.176
#Sta/Elev= 28
       0 1035.57     9.4 1032.39    18.7 1029.09      28 1025.92    37.4 1022.38
    74.8  1006.6    84.2 1004.25    93.5 1003.45   208.9  997.46   218.5  996.86
   228.1  996.16   237.7   995.1   247.3  994.51   256.9  995.55   264.3  997.47
   276.2 1000.52   285.8 1002.58   295.4 1004.32   305.2 1005.56     315 1006.49
   324.8 1007.07   334.7 1007.24   344.5 1007.58   354.3 1008.67   364.1 1010.18
     374  1010.7   383.8 1009.45   393.6 1007.25
#Mann= 3 , 0 , 0
       0      .1       0   247.3    .045       0   264.3      .1       0
Bank Sta=247.3,264.3
XS Rating Curve= 0 ,0
Exp/Cntr=0.3,0.1

Type RM Length L Ch R = 1 ,8647.4  ,236.1,234.9,233.6
XS GIS Cut Line= 3
     1887655.516      511163.072     1887649.005      511299.791
     1887715.412      511429.999
#Sta/Elev= 25
       0  1014.4    19.6 1012.09    29.3 1011.03    58.7 1007.99      88 1004.51
    97.8 1003.49   107.5 1002.62   117.3 1001.89   127.1  1000.8   136.9  998.78
   146.6  994.95  152.26  993.44   156.4  991.97   166.1  991.63   174.8   994.2
   175.8   994.5   185.6  999.16   195.3 1001.94   205.1 1002.97   214.8 1004.24
   224.6 1005.92   244.1  1009.6   253.8 1011.54   273.3 1015.73     283 1017.95
#Mann= 3 , 0 , 0
       0      .1       0  152.26    .045       0   174.8      .1       0
Bank Sta=152.26,174.8
XS Rating Curve= 0 ,0
Exp/Cntr=0.3,0.1

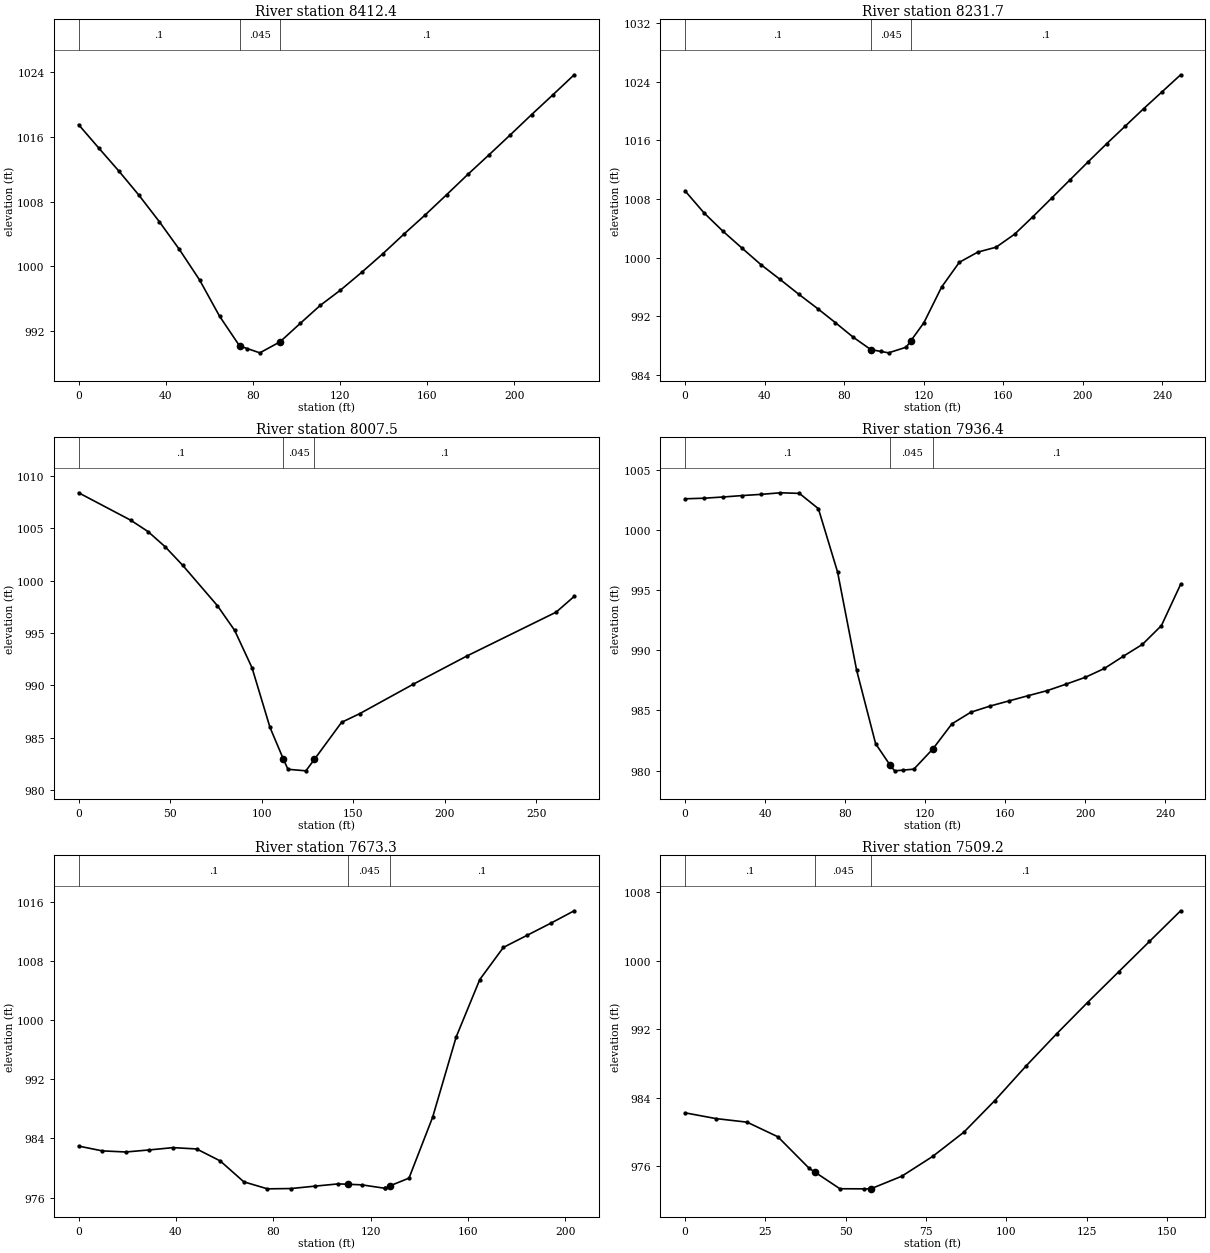
Type RM Length L Ch R = 1 ,8412.4  ,182.1,180.8,178.6
XS GIS Cut Line= 3
     1887423.745      511377.916     1887483.641      511482.083
     1887551.349      511565.416
#Sta/Elev= 27
       0 1017.52     9.2 1014.65    18.5 1011.78    27.7  1008.8      37 1005.55
    46.2 1002.12    55.5  998.34    64.7  993.85    73.9  990.17    77.5  989.84
    83.2  989.32    92.4  990.67    92.5  990.69   101.7  992.95   110.9  995.18
   120.2  997.07   129.9  999.26   139.7 1001.58   149.4 1004.01   159.2 1006.39
     169 1008.88   178.7 1011.38   188.5 1013.82   198.2 1016.27     208 1018.78
   217.8 1021.23   227.5 1023.69
#Mann= 3 , 0 , 0
       0      .1       0    73.9    .045       0    92.5      .1       0
Bank Sta=73.9,92.5
XS Rating Curve= 0 ,0
Exp/Cntr=0.3,0.1

Type RM Length L Ch R = 1 ,8231.7  ,241.2,224.1,207.3
XS GIS Cut Line= 4
     1887302.651      511489.895     1887326.089      511552.395
     1887366.453      511610.989      1887464.11      511664.374
#Sta/Elev= 30
       0 1009.09     9.5  1006.1    19.1 1003.58    28.6  1001.3    38.1  999.05
    47.7  997.04    57.2     995    66.8  993.02    75.6  991.13    84.5  989.16
    93.4  987.46    98.5  987.21   102.3  987.02   111.2  987.79   113.5  988.65
   120.1  991.13     129  995.99   137.9  999.36   147.2 1000.75   156.4 1001.42
   165.7 1003.19     175  1005.6   184.3  1008.1   193.6 1010.61   202.8 1013.09
   212.1 1015.55   221.4 1017.94   230.6  1020.3   239.9 1022.61   249.2 1024.92
#Mann= 3 , 0 , 0
       0      .1       0    93.4    .045       0   113.5      .1       0
Bank Sta=93.4,113.5
XS Rating Curve= 0 ,0
Exp/Cntr=0.3,0.1

Type RM Length L Ch R = 1 ,8007.5  ,75.3,71.1,66.9
XS GIS Cut Line= 4
     1887156.818      511666.978     1887206.297      511747.708
     1887263.589      511760.728     1887366.453      511704.739
#Sta/Elev= 19
       0 1008.41    28.4 1005.79    37.9  1004.7    47.3 1003.24    56.8 1001.48
    75.8  997.61    85.2  995.25    94.7  991.67   104.5  985.97  111.87  982.91
   114.3  981.97   124.1  981.82   128.8  982.93   143.6  986.46   153.4  987.28
   182.7   990.1     212   992.8   260.8     997   270.6   998.5
#Mann= 3 , 0 , 0
       0      .1       0  111.87    .045       0   128.8      .1       0
Bank Sta=111.87,128.8
XS Rating Curve= 0 ,0
Exp/Cntr=0.3,0.1

Type RM Length L Ch R = 1 ,7936.4  ,246.7,263.2,279.3
XS GIS Cut Line= 2
     1887109.943      511819.322     1887357.339      511828.437
#Sta/Elev= 30
       0 1002.57     9.5 1002.62      19 1002.72    28.6 1002.84    38.1 1002.94
    47.6 1003.07    57.1 1003.02    66.6 1001.75    76.2  996.48    85.7  988.34
    95.2  982.23  102.52  980.43   104.7  979.98   108.9  980.04   114.3  980.12
   123.8   981.8   123.9  981.82   133.3  983.88   142.8  984.85   152.4  985.36
   161.9  985.79   171.4  986.22   180.9  986.64   190.4  987.18     200  987.75
   209.5  988.48     219   989.5   228.5  990.48     238  992.04   247.6  995.47
#Mann= 3 , 0 , 0
       0      .1       0  102.52    .045       0   123.9      .1       0
Bank Sta=102.52,123.9
XS Rating Curve= 0 ,0
Exp/Cntr=0.3,0.1

Type RM Length L Ch R = 1 ,7673.3  ,137,164.1,191.5
XS GIS Cut Line= 2
      1887133.38      512002.916     1887284.422      512139.635
#Sta/Elev= 25
       0  982.97     9.7  982.32    19.4  982.17    29.1  982.45    38.8  982.76
    48.5  982.58    58.2  980.96    67.9  978.13    77.6  977.18    87.3  977.22
      97  977.54   106.7  977.85   110.8   977.8   116.4  977.72   125.8  977.26
   126.1  977.25  127.99  977.59   135.8  978.63   145.5  986.86   155.2  997.75
   164.9 1005.52   174.6 1009.87   184.3  1011.5     194 1013.13   203.7 1014.83
#Mann= 3 , 0 , 0
       0      .1       0   110.8    .045       0  127.99      .1       0
Bank Sta=110.8,127.99
XS Rating Curve= 0 ,0
Exp/Cntr=0.3,0.1

Type RM Length L Ch R = 1 ,7509.2  ,286.4,271.1,255.6
XS GIS Cut Line= 2
      1887095.62      512038.072     1887038.328      512181.301
#Sta/Elev= 19
       0  982.21     9.6  981.54    19.3  981.12    28.9  979.41    38.6  975.74
    40.6  975.24    48.2  973.34    55.6  973.33    57.8  973.33    67.5  974.81
    77.1  977.12    86.8  979.95    96.4  983.63   106.1  987.66   115.7  991.45
   125.3   995.1     135  998.69   144.6 1002.24   154.3 1005.82
#Mann= 3 , 0 , 0
       0      .1       0    40.6    .045       0    57.8      .1       0
Bank Sta=40.6,57.8
XS Rating Curve= 0 ,0
Exp/Cntr=0.3,0.1

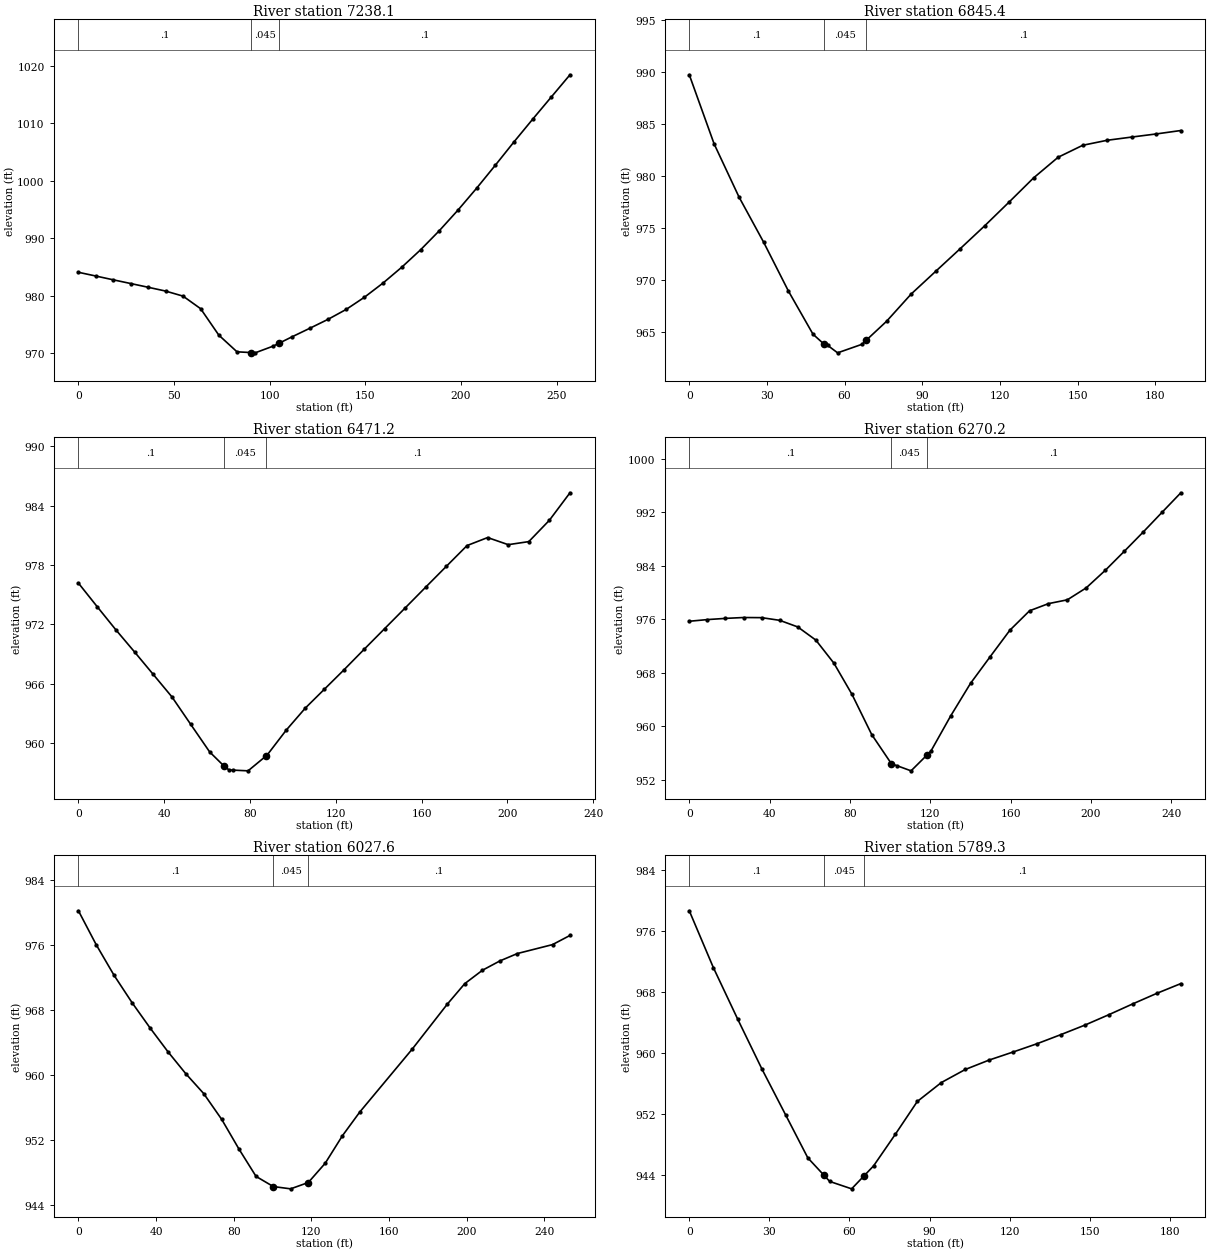
Type RM Length L Ch R = 1 ,7238.1  ,392.5,392.7,392.5
XS GIS Cut Line= 4
      1886814.37      511982.083     1886811.766      512045.885
     1886836.505      512127.916     1886857.339      512233.385
#Sta/Elev= 30
       0  984.05     9.1   983.4    18.2  982.74    27.4  982.09    36.5  981.44
    45.6  980.78    54.7   979.9    63.9  977.71    73.4  973.11    82.9  970.21
      90  970.08    92.4  970.03   101.9  971.21     105  971.72   111.5  972.79
     121  974.31   130.5  975.86     140  977.59   149.5   979.7   159.3  982.19
   169.1  984.95   178.9  987.97   188.6  991.26   198.4  994.86   208.2  998.69
     218  1002.7   227.7 1006.74   237.5  1010.7   247.3 1014.59     257 1018.43
#Mann= 3 , 0 , 0
       0      .1       0      90    .045       0     105      .1       0
Bank Sta=90,105
XS Rating Curve= 0 ,0
Exp/Cntr=0.3,0.1

Type RM Length L Ch R = 1 ,6845.4  ,374.6,374.2,374
XS GIS Cut Line= 3
     1886426.349      512073.228      1886432.86      512110.989
     1886478.432       512255.52
#Sta/Elev= 24
       0  989.77     9.6  983.12    19.2  978.02    28.7  973.68    38.3  968.97
    47.8  964.82    51.9   963.9    53.4  963.76    57.3  963.03    66.7  963.85
    68.4  964.25    76.2  966.06    85.7  968.68    95.2  970.87   104.6  973.03
   114.1  975.24   123.6  977.54     133  979.85   142.5  981.84     152  982.99
   161.4  983.47   170.9  983.78   180.4  984.08   189.9  984.41
#Mann= 3 , 0 , 0
       0      .1       0    51.9    .045       0    68.4      .1       0
Bank Sta=51.9,68.4
XS Rating Curve= 0 ,0
Exp/Cntr=0.3,0.1

Type RM Length L Ch R = 1 ,6471.2  ,206.1,201,194.8
XS GIS Cut Line= 4
     1886061.766      512139.635     1886066.974      512191.718
      1886089.11      512259.426     1886129.474      512357.083
#Sta/Elev= 29
       0  976.16     8.7  973.79    17.4  971.45    26.2  969.19    34.9  966.92
    43.6  964.65    52.3  961.89    61.2  959.08   67.76  957.68    70.2  957.26
    72.3  957.24    79.1  957.17    87.3  958.64      88  958.77    96.9  961.29
   105.8  963.52   114.7  965.43   123.6  967.34   133.2  969.46   142.8  971.56
   152.4  973.66     162  975.77   171.6  977.87   181.2  979.96   190.8  980.77
   200.4  980.05     210  980.36   219.6  982.52   229.2   985.3
#Mann= 3 , 0 , 0
       0      .1       0   67.76    .045       0    87.3      .1       0
Bank Sta=67.76,87.3
XS Rating Curve= 0 ,0
Exp/Cntr=0.3,0.1

Type RM Length L Ch R = 1 ,6270.2  ,239.3,242.6,246
XS GIS Cut Line= 4
     1885828.693      512264.635     1885900.307      512302.395
     1885948.485      512376.614     1885978.432      512445.624
#Sta/Elev= 29
       0   975.7       9  975.95      18  976.13      27  976.26      36  976.24
      45  975.84      54  974.85      63  972.88      72  969.42      81  964.75
    90.8  958.74   100.6  954.37   103.3  954.08   110.4   953.3   118.3  955.66
   120.3  956.26   130.1  961.51     140   966.4   149.8   970.4   159.6  974.36
   169.4  977.27   178.8  978.34   188.2  978.91   197.6   980.7   207.1  983.33
   216.5  986.16   225.9  989.04   235.3     992   244.7  994.94
#Mann= 3 , 0 , 0
       0      .1       0   100.6    .045       0   118.3      .1       0
Bank Sta=100.6,118.3
XS Rating Curve= 0 ,0
Exp/Cntr=0.3,0.1

Type RM Length L Ch R = 1 ,6027.6  ,243.4,238.2,232.5
XS GIS Cut Line= 4
     1885632.078      512354.478     1885686.766      512403.958
     1885715.412      512469.062     1885740.151      512574.531
#Sta/Elev= 25
       0  980.26     9.2  976.06    18.4  972.29    27.7  968.91    36.9  965.82
    46.1  962.89    55.3  960.18    64.5  957.74    73.8  954.55    82.6  950.93
    91.5  947.52   100.4  946.27   109.3  945.99   118.4  946.77   127.1  949.14
     136  952.54   144.9  955.45     172  963.23     190  968.75     199  971.28
   208.1  972.93   217.1  974.08   226.1  974.99   244.2  976.09   253.2  977.22
#Mann= 3 , 0 , 0
       0      .1       0   100.4    .045       0   118.4      .1       0
Bank Sta=100.4,118.4
XS Rating Curve= 0 ,0
Exp/Cntr=0.3,0.1

Type RM Length L Ch R = 1 ,5789.3  ,200.9,186.5,170.1
XS GIS Cut Line= 4
     1885456.297      512517.239     1885484.943      512539.374
     1885514.891      512578.437     1885606.037      512616.197
#Sta/Elev= 24
       0  978.63       9  971.19    18.1  964.44    27.2  957.88    36.2  951.78
    44.4  946.22    50.5  943.92    52.6  943.13    60.8  942.16    65.5  943.88
      69  945.16    77.2  949.33    85.4  953.62    94.4   956.1   103.4  957.82
   112.3  959.05   121.3  960.11   130.3   961.2   139.2  962.39   148.2  963.64
   157.2  965.01   166.1  966.42   175.1   967.8   184.1  969.08
#Mann= 3 , 0 , 0
       0      .1       0    50.5    .045       0    65.5      .1       0
Bank Sta=50.5,65.5
XS Rating Curve= 0 ,0
Exp/Cntr=0.3,0.1

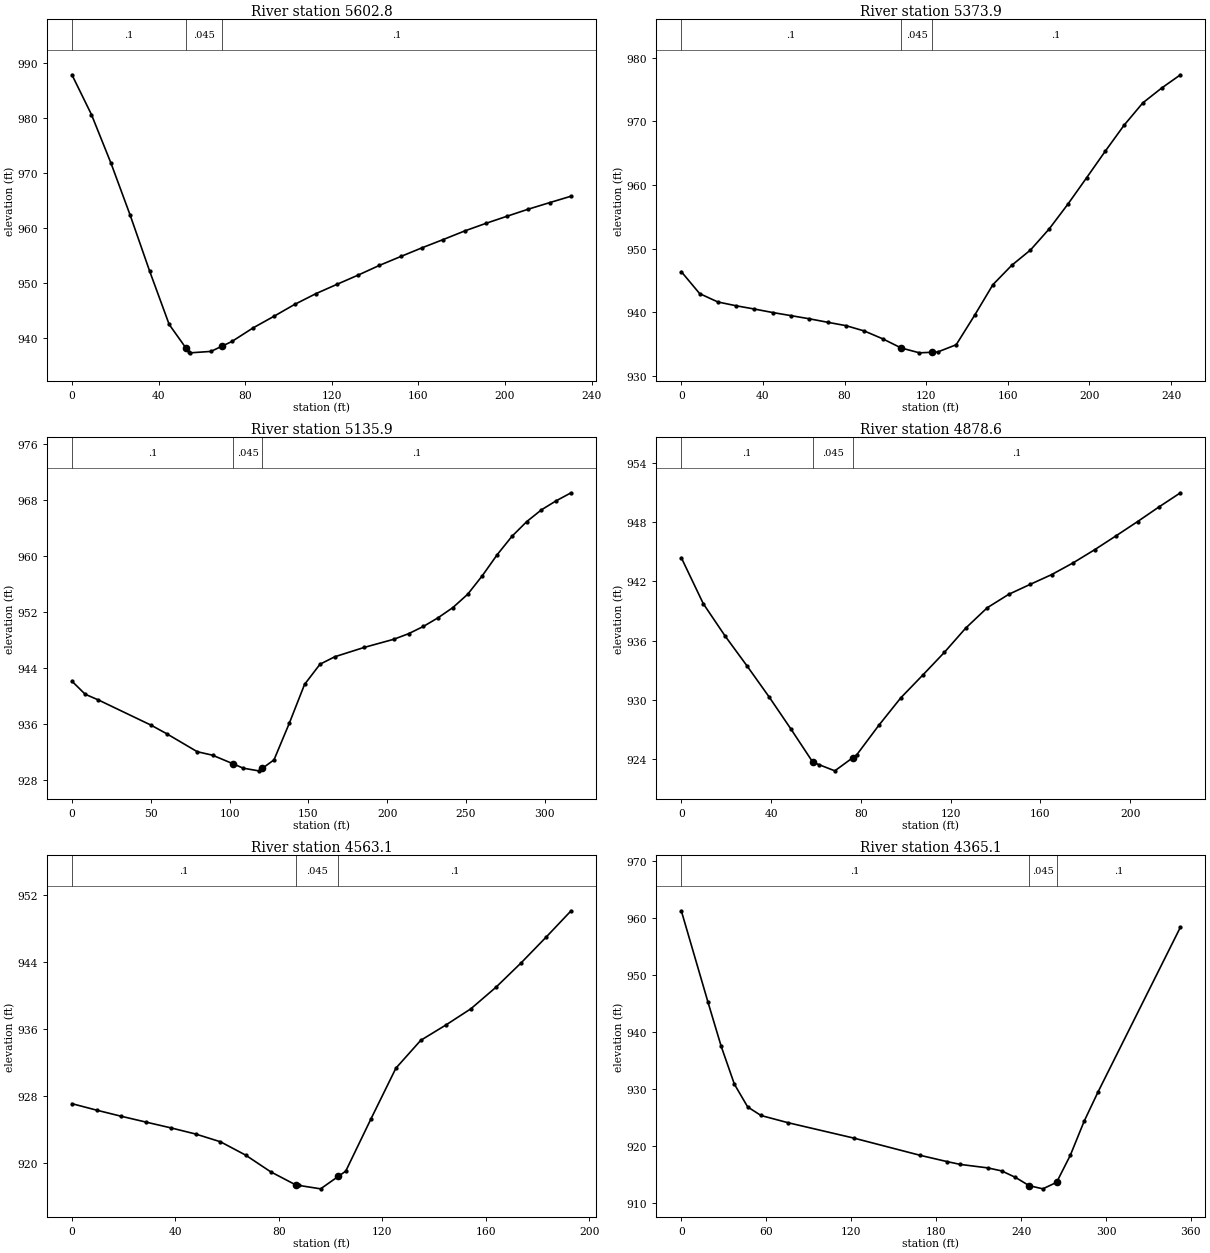
Type RM Length L Ch R = 1 ,5602.8  ,217.2,228.9,242.2
XS GIS Cut Line= 4
      1885345.62      512683.906     1885384.682      512706.041
     1885451.089      512719.062     1885568.276      512732.083
#Sta/Elev= 28
       0  987.79       9  980.57      18  971.76    26.9  962.27    35.9   952.1
    44.9  942.43    52.7  938.11    54.2  937.48    54.6  937.27    64.2  937.53
    69.2  938.46    73.9  939.34    83.6  941.79    93.2  943.89   102.9  946.08
   112.6  948.01   122.4  949.72   132.2   951.4     142  953.16   151.9  954.78
   161.7  956.36   171.5  957.86   181.4  959.42   191.2   960.8     201   962.1
   210.8  963.38   220.6  964.56   230.5  965.73
#Mann= 3 , 0 , 0
       0      .1       0    52.7    .045       0    69.2      .1       0
Bank Sta=52.7,69.2
XS Rating Curve= 0 ,0
Exp/Cntr=0.3,0.1

Type RM Length L Ch R = 1 ,5373.9  ,211.6,238,263.9
XS GIS Cut Line= 4
      1885307.86      512834.947     1885337.807      512900.051
     1885395.099      512957.343     1885468.016      513013.333
#Sta/Elev= 30
       0  946.37       9  942.92    17.9  941.61    26.9  941.01    35.8   940.5
    44.8  939.95    53.8  939.46    62.7  938.97    71.7  938.42    80.7  937.89
    89.7  937.05    98.7  935.82   107.7  934.39   107.8  934.38   116.7  933.62
   122.8  933.71   125.7  933.76   134.7  934.89   143.7   939.5   152.7  944.33
   161.9  947.36   171.1  949.77   180.3  953.09   189.5     957   198.6  961.11
   207.8  965.31     217  969.38   226.2  972.89   235.4  975.21   244.6  977.29
#Mann= 3 , 0 , 0
       0      .1       0   107.8    .045       0   122.8      .1       0
Bank Sta=107.8,122.8
XS Rating Curve= 0 ,0
Exp/Cntr=0.3,0.1

Type RM Length L Ch R = 1 ,5135.9  ,277.2,257.3,239.4
XS GIS Cut Line= 4
     1885210.203      512870.103     1885184.162      512913.072
     1885146.401      513013.333     1885169.839      513170.885
#Sta/Elev= 30
       0   942.1     8.4  940.23    16.8  939.41    50.2   935.8      60  934.59
    79.5     932    89.2   931.5     102  930.29   108.7  929.64   118.4  929.26
   120.9  929.63   128.2  930.83   137.9  936.07   147.6  941.64   157.4  944.53
   166.8   945.6   185.5  946.94   204.2   948.1   213.6   948.9     223  949.94
   232.3  951.18   241.7  952.64   251.1  954.55   260.4  957.21   269.8  960.21
   279.2  962.85   288.6  964.96   297.9  966.64   307.3  967.94   316.7  969.08
#Mann= 3 , 0 , 0
       0      .1       0     102    .045       0   120.9      .1       0
Bank Sta=102,120.9
XS Rating Curve= 0 ,0
Exp/Cntr=0.3,0.1

Type RM Length L Ch R = 1 ,4878.6  ,311.6,315.4,317.7
XS GIS Cut Line= 4
     1884874.266       512967.76      1884914.63      512995.103
      1884939.37      513048.489      1884995.36      513148.749
#Sta/Elev= 26
       0  944.39     9.8  939.74    19.5  936.48    29.2  933.48      39  930.36
    48.8  927.09    58.6  923.72    61.3  923.48    68.4  922.85    76.3  924.16
    78.2  924.48      88  927.45    97.8  930.23   107.6  932.53   117.2  934.82
   126.7  937.27   136.3  939.33   145.9  940.69   155.4  941.69     165  942.68
   174.6  943.87   184.2   945.2   193.7   946.6   203.3  948.04   212.9  949.53
   222.4  950.95
#Mann= 3 , 0 , 0
       0      .1       0    58.6    .045       0    76.3      .1       0
Bank Sta=58.6,76.3
XS Rating Curve= 0 ,0
Exp/Cntr=0.3,0.1

Type RM Length L Ch R = 1 ,4563.1  ,200.3,198.1,195.6
XS GIS Cut Line= 3
     1884649.005      513086.249     1884645.099      513143.541
     1884690.672      513271.145
#Sta/Elev= 23
       0  927.06     9.6  926.28    19.1  925.55    28.7  924.85    38.3  924.16
    47.8  923.43    57.4   922.5    67.1  920.91    76.8  918.91    86.5  917.34
    87.9  917.27    96.1  916.87   102.9  918.35   105.8  918.98   115.5   925.2
   125.2  931.31   134.8  934.64   144.5  936.47   154.2  938.42   163.9     941
   173.6  943.91   183.2  946.97   192.9  950.14
#Mann= 3 , 0 , 0
       0      .1       0    86.5    .045       0   102.9      .1       0
Bank Sta=86.5,102.9
XS Rating Curve= 0 ,0
Exp/Cntr=0.3,0.1

Type RM Length L Ch R = 1 ,4365.1  ,261.1,257.2,251.8
XS GIS Cut Line= 3
     1884464.544      513018.107     1884460.203      513215.156
      1884526.61      513355.781
#Sta/Elev= 21
       0   961.3    18.8  945.28    28.2  937.46    37.5  930.82    46.9  926.82
    56.3  925.32    75.1  924.07     122  921.34   168.9  918.31   187.7  917.22
   197.1  916.72   216.5  916.11   226.3  915.58     236  914.45   245.7  912.99
   255.4  912.43   265.1  913.57   274.8  918.33   284.6  924.33   294.3  929.42
   352.6  958.43
#Mann= 3 , 0 , 0
       0      .1       0   245.7    .045       0   265.1      .1       0
Bank Sta=245.7,265.1
XS Rating Curve= 0 ,0
Exp/Cntr=0.3,0.1

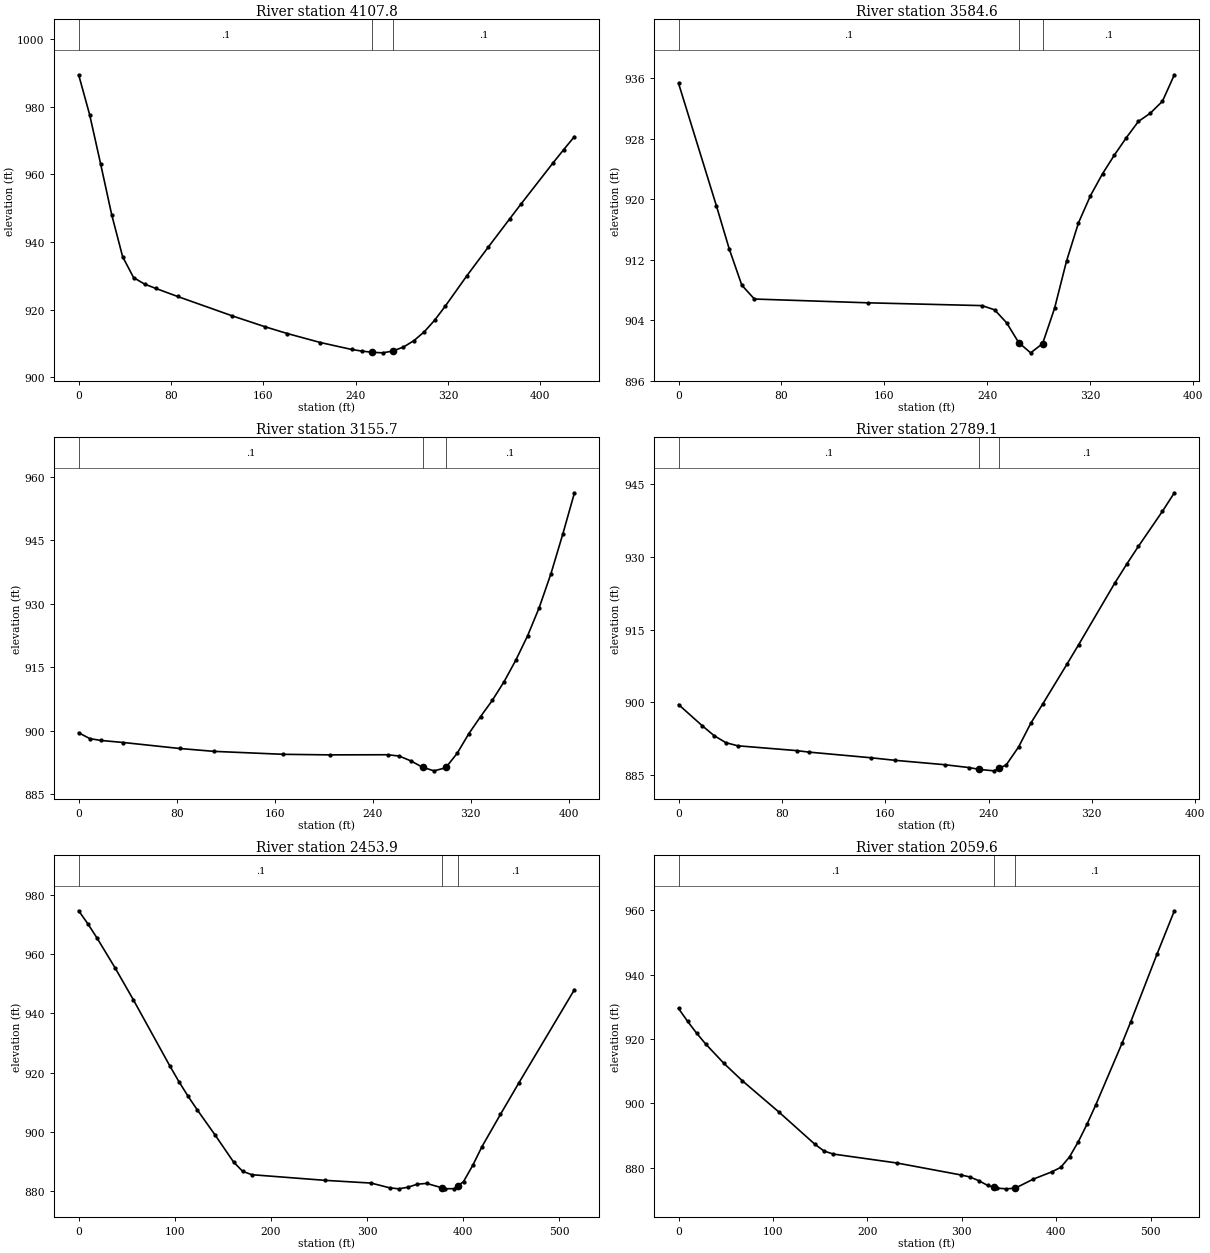
Type RM Length L Ch R = 1 ,4107.8  ,517.3,523.2,529.5
XS GIS Cut Line= 4
      1884131.21      513088.419     1884218.016      513278.958
     1884271.401      513362.291     1884323.485      513471.666
#Sta/Elev= 30
       0  989.44     9.5  977.68      19  963.17    28.6  948.13    38.1  935.68
    47.6   929.5    57.1  927.58    66.6  926.34    85.7  923.93   133.2  918.18
   161.8  914.94   180.8  912.97   209.4  910.32   236.4  908.27   245.4  907.78
   254.4  907.43   263.4  907.27     272   907.8   281.4  908.99   290.4  910.87
   299.4  913.49   308.4  916.92   317.7  921.12   336.3  930.05   354.9  938.55
   373.6  946.96   382.9  951.12   410.8  963.34   420.2  967.34   429.5  971.19
#Mann= 3 , 0 , 0
       0      .1       0   254.4    .045       0     272      .1       0
Bank Sta=254.4,272
XS Rating Curve= 0 ,0
Exp/Cntr=0.3,0.1

Type RM Length L Ch R = 1 ,3584.6  ,427.3,428.9,430.3
XS GIS Cut Line= 3
     1883737.547      513390.937      1883839.11      513614.895
     1883889.891      513745.103
#Sta/Elev= 23
       0  935.35    29.5  919.11    39.4  913.45    49.2  908.64      59   906.8
   147.6   906.3   236.1  905.93   245.9  905.37   255.2  903.66   264.6  901.04
   273.9  899.68   283.2   900.9   292.5  905.57   301.8  911.82   311.1  916.88
   320.4  920.47   329.8  923.38   339.1  925.87   348.4  928.17   357.7   930.3
     367   931.4   376.4  932.97   385.7  936.48
#Mann= 3 , 0 , 0
       0      .1       0   264.6    .045       0   283.2      .1       0
Bank Sta=264.6,283.2
XS Rating Curve= 0 ,0
Exp/Cntr=0.3,0.1

Type RM Length L Ch R = 1 ,3155.7  ,355.5,366.6,377.6
XS GIS Cut Line= 4
     1883397.703      513502.916     1883389.891      513594.062
     1883458.901      513810.208      1883495.36      513888.333
#Sta/Elev= 26
       0   899.5     9.2  898.11    18.3  897.68    36.6   897.2    82.3  895.79
   110.4  895.11   167.1  894.41   204.9  894.28   252.2  894.31   261.6     894
   271.1  892.86   280.6  891.36     290  890.51   299.5  891.23   299.7   891.3
   308.9  894.66   318.4  899.29     328  903.33   337.5  907.13   347.1  911.53
   356.7  916.62   366.3  922.37   375.8  929.03   385.4  937.06     395  946.34
   404.6  956.17
#Mann= 3 , 0 , 0
       0      .1       0   280.6    .045       0   299.7      .1       0
Bank Sta=280.6,299.7
XS Rating Curve= 0 ,0
Exp/Cntr=0.3,0.1

Type RM Length L Ch R = 1 ,2789.1  ,335.6,335.2,335
XS GIS Cut Line= 4
     1883130.776      513608.385     1883122.964      513699.531
     1883090.412      513877.916      1883070.88      513987.291
#Sta/Elev= 25
       0  899.51    18.3  895.14    27.4  893.11    36.6  891.64    45.7  890.99
    91.5  889.99     101  889.68   148.7  888.52   167.8  887.98     206  887.08
   225.1  886.48     233   886.1   244.2  885.81     248   886.3   253.7  887.03
   263.3  890.75   272.8  895.68   282.1  899.68   300.6  907.79   309.8  911.89
   337.6  924.53   346.9  928.48   356.1  932.22   374.7  939.46   383.9  943.27
#Mann= 3 , 0 , 0
       0      .1       0     233    .045       0     248      .1       0
Bank Sta=233,248
XS Rating Curve= 0 ,0
Exp/Cntr=0.3,0.1

Type RM Length L Ch R = 1 ,2453.9  ,406.4,394.3,381.5
XS GIS Cut Line= 4
     1882862.981      513403.524     1882794.839       513630.52
     1882766.193      513801.093     1882757.078      513906.562
#Sta/Elev= 30
       0   974.8     9.5  970.43      19  965.63    37.9  955.46    56.9  944.65
    94.8  922.27   104.3  916.92   113.8  911.98   123.2  907.44   142.2  898.71
   161.2  889.67   170.6  886.53   180.1  885.38   256.2  883.47   304.3  882.54
   323.5  880.94   333.1  880.59   342.7  881.15   352.3  882.16   361.9  882.43
  377.99  880.94   381.1  880.63   390.8  880.64   394.8  881.65   400.4  883.06
     410  888.56   419.6  894.91   438.8  905.82   458.1  916.57   515.8  948.09
#Mann= 3 , 0 , 0
       0      .1       0  377.99    .045       0   394.8      .1       0
Bank Sta=377.99,394.8
XS Rating Curve= 0 ,0
Exp/Cntr=0.3,0.1

Type RM Length L Ch R = 1 ,2059.6  ,309.2,310.2,311
XS GIS Cut Line= 4
     1882282.252      513434.774     1882410.724      513682.603
     1882458.901      513798.489     1882499.266       513911.77
#Sta/Elev= 30
       0  929.51     9.6   925.5    19.2  921.82    28.9  918.42    48.1  912.44
    67.4  907.08   105.9  897.42   144.4   887.3     154  885.22   163.6  884.28
     231   881.5   298.5   877.8   308.1  877.18   317.8     876   327.4   874.5
   333.7  873.98   337.1   873.7   346.7  873.46   356.4  873.66   375.7   876.5
     395  878.72   404.6  880.13   413.9  883.39   423.2   888.1   432.4  893.54
   441.6  899.49   469.4  918.64   478.7  925.35   506.4  946.32   524.9  959.88
#Mann= 3 , 0 , 0
       0      .1       0   333.7    .045       0   356.4      .1       0
Bank Sta=333.7,356.4
XS Rating Curve= 0 ,0
Exp/Cntr=0.3,0.1