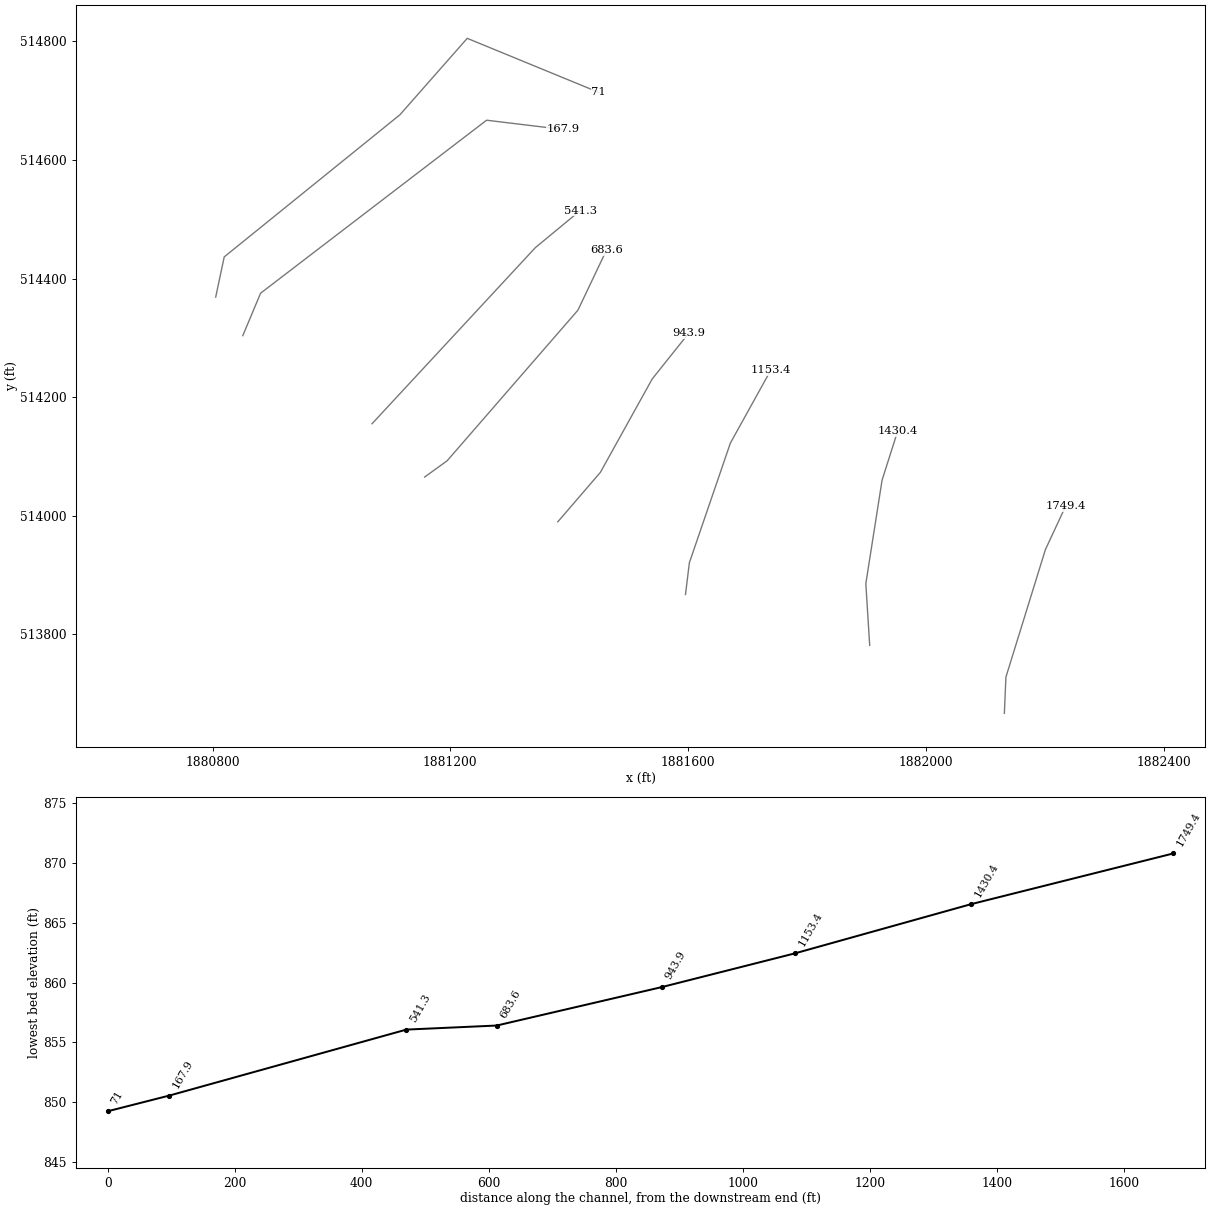
HEC-RAS study HORSEFRK.prj: HORSEFRK

--- HORSEFRK.g01 (geometry) --- (continued)

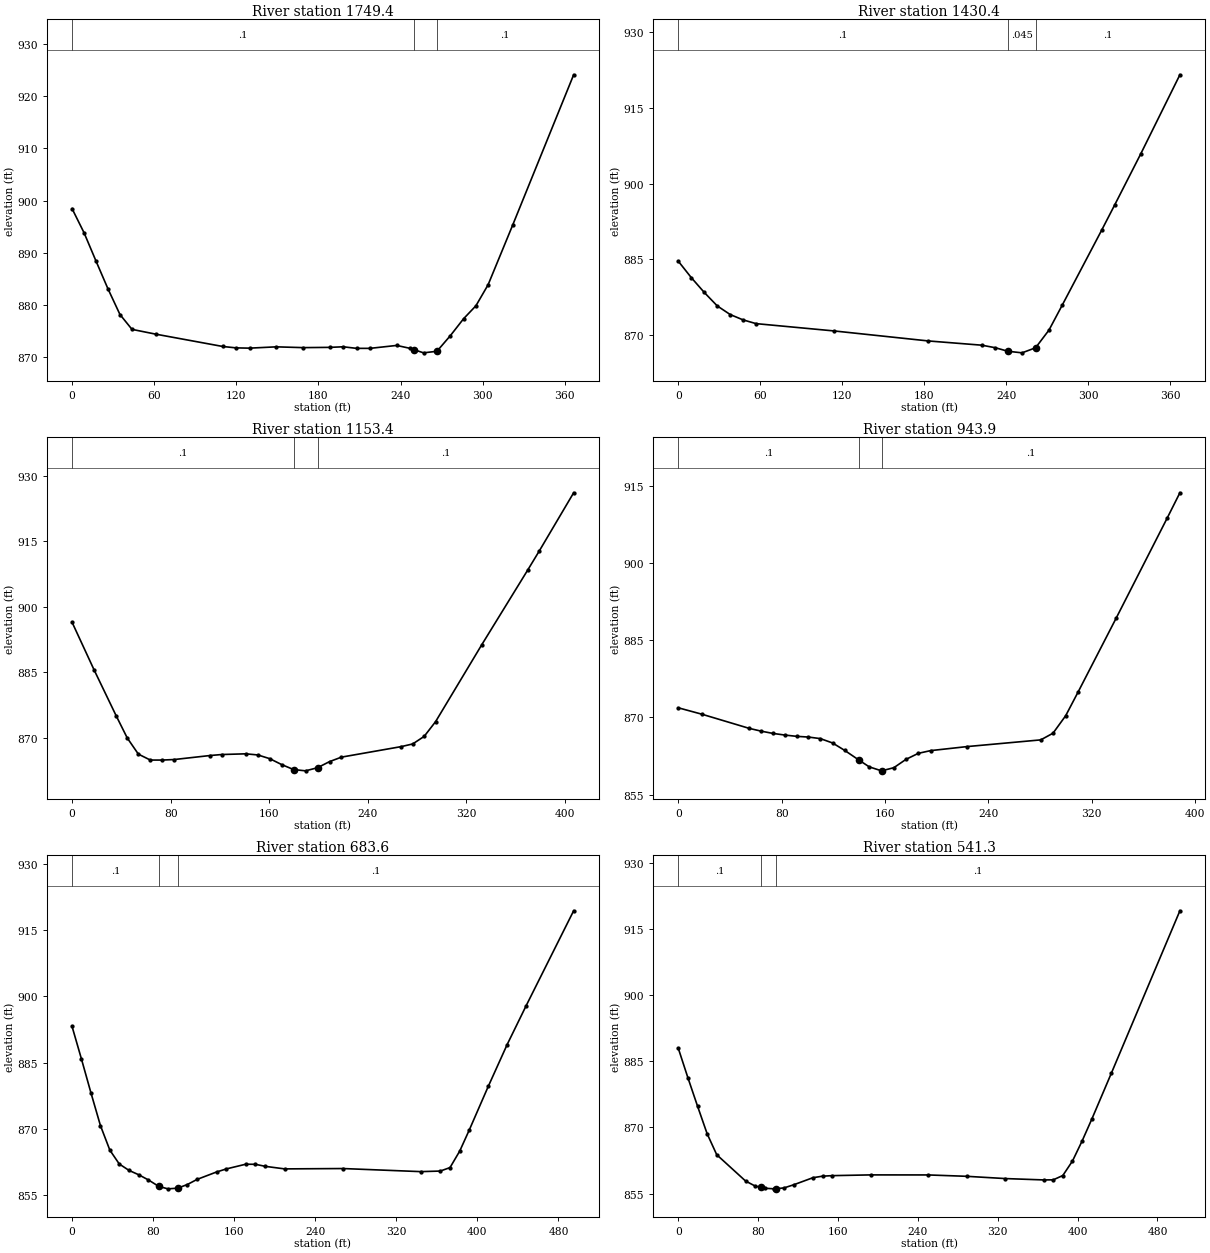
Type RM Length L Ch R = 1 ,1749.4  ,315.3,319,322.1
XS GIS Cut Line= 4
     1882132.078      513666.978     1882134.682      513728.176
     1882201.089       513943.02     1882234.943      514015.937
#Sta/Elev= 27
       0  898.46     8.8  893.81    17.5   888.4    26.2   883.1      35  878.15
    43.8   875.3    61.2  874.38   110.1  872.02   119.9  871.75   129.7   871.7
   149.2  871.95   168.8   871.8   188.4  871.85   198.1  871.96   207.9  871.66
   217.7  871.66   237.2  872.22     247  871.66   249.6  871.43   256.8   870.8
   266.6   871.1   276.4  874.09   286.1  877.35   295.1  879.83     304  883.86
   321.9  895.27   366.5  924.13
#Mann= 3 , 0 , 0
       0      .1       0   249.6    .045       0   266.6      .1       0
Bank Sta=249.6,266.6
XS Rating Curve= 0 ,0
Exp/Cntr=0.3,0.1

Type RM Length L Ch R = 1 ,1430.4  ,281.6,277,272.3
XS GIS Cut Line= 4
     1881905.516      513781.562     1881899.005      513885.728
     1881926.349      514060.208     1881952.391      514142.239
#Sta/Elev= 20
       0  884.65     9.5  881.41      19  878.48    28.5  875.82      38  874.11
    47.4  873.06    56.9  872.32   114.2  870.87   182.9   868.9   222.1  868.06
   231.9  867.56   241.2  866.86   251.5  866.55   261.4  867.55   271.2  871.04
     281  876.02   309.7  890.75   319.2  895.72   338.4  905.88     367  921.48
#Mann= 3 , 0 , 0
       0      .1       0   241.2    .045       0   261.4      .1       0
Bank Sta=241.2,261.4
XS Rating Curve= 0 ,0
Exp/Cntr=0.3,0.1

Type RM Length L Ch R = 1 ,1153.4  ,212.7,209.5,205.9
XS GIS Cut Line= 4
      1881595.62      513867.499      1881602.13      513920.885
     1881671.141      514122.708     1881738.849      514245.103
#Sta/Elev= 27
       0  896.48    17.9  885.55    35.8  875.05    44.8  869.96    53.8  866.27
    63.5  864.91    73.2  864.91    82.9  865.03     112  865.95   121.6  866.18
     141  866.34   150.7  866.08   160.4  865.23   170.1  863.87   179.8  862.73
   189.5  862.44   199.2  863.16   208.9  864.55   218.6  865.58   267.1  867.99
   276.4   868.6   285.7  870.33     295  873.72   332.4  891.31   369.6  908.38
     379  912.76     407  926.14
#Mann= 3 , 0 , 0
       0      .1       0   179.8    .045       0   199.2      .1       0
Bank Sta=179.8,199.2
XS Rating Curve= 0 ,0
Exp/Cntr=0.3,0.1

Type RM Length L Ch R = 1 ,943.9   ,264.6,260.3,255.2
XS GIS Cut Line= 4
     1881380.776      513989.895     1881452.391      514073.228
      1881539.63      514230.781     1881600.828      514307.603
#Sta/Elev= 26
       0  871.88    18.3  870.63    54.9  867.88    64.1  867.34    73.2   866.9
    82.4  866.58    91.6  866.33   100.7  866.19   109.9  865.89   119.4  865.04
   128.8  863.59     140  861.68   147.8  860.39   157.3  859.62   166.8  860.23
   176.2  861.85   185.7  863.02   195.2  863.55   223.6  864.34   280.5  865.64
     290  866.94   299.8  870.34   309.6  875.04   339.1  889.43   378.4   908.8
   388.2   913.7
#Mann= 3 , 0 , 0
       0      .1       0     140    .045       0   157.3      .1       0
Bank Sta=140,157.3
XS Rating Curve= 0 ,0
Exp/Cntr=0.3,0.1

Type RM Length L Ch R = 1 ,683.6   ,139.6,142.3,147.5
XS GIS Cut Line= 4
     1881156.818      514065.416     1881194.578       514092.76
      1881414.63      514346.666     1881462.807      514448.228
#Sta/Elev= 30
       0   893.2     9.3   885.8    18.6  878.19      28  870.74    37.3  865.17
    46.6  862.03    56.2  860.58    65.8  859.59    75.4  858.41    85.6  856.95
    94.6   856.4   104.2  856.55   113.8  857.38   123.4  858.54   142.6  860.22
   152.2  860.91   171.4  861.98     181  861.96   190.6   861.5   209.8  860.92
   267.4     861   344.2   860.3   363.4  860.43     373  861.22   382.6  864.97
     392  869.74   410.7   879.6   429.4  889.11   448.2  897.94     495  919.42
#Mann= 3 , 0 , 0
       0      .1       0    85.6    .045       0   104.2      .1       0
Bank Sta=85.6,104.2
XS Rating Curve= 0 ,0
Exp/Cntr=0.3,0.1

Type RM Length L Ch R = 1 ,541.3   ,379.7,373.4,363.8
XS GIS Cut Line= 3
     1881068.276       514155.26     1881343.016      514452.135
     1881418.537      514514.635
#Sta/Elev= 28
       0  887.91     9.6  881.25    19.3  874.78    28.9  868.54    38.5  863.79
    67.4  857.83      77  856.69    82.7   856.4    86.7  856.19    96.3  856.06
    97.7  856.09   105.9  856.27   115.6  856.98   134.8  858.58   144.5  858.93
   154.1  859.05   192.6  859.22   250.4  859.21   288.9   858.9   327.4  858.39
     366  858.08   375.6   858.1   385.2  859.08   394.9  862.37   404.5  866.89
   414.3  871.89   433.9  882.31   502.5  919.09
#Mann= 3 , 0 , 0
       0      .1       0    82.7    .045       0    97.7      .1       0
Bank Sta=82.7,97.7
XS Rating Curve= 0 ,0
Exp/Cntr=0.3,0.1

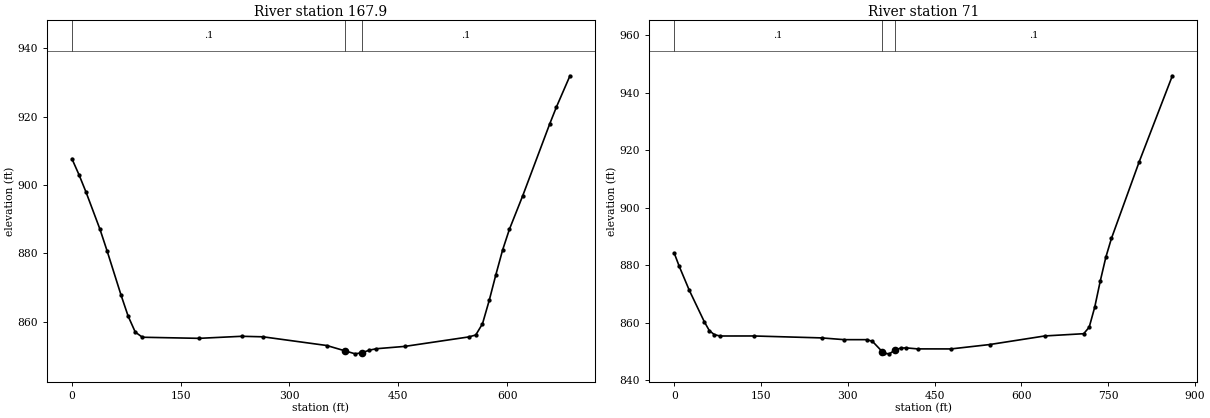
Type RM Length L Ch R = 1 ,167.9   ,95.9,96.9,96.8
XS GIS Cut Line= 4
     1880850.828      514303.697     1880880.776      514375.312
     1881260.985      514666.978     1881389.891      514651.353
#Sta/Elev= 30
       0  907.71     9.7  903.06    19.4  897.97    38.8  886.98    48.5  880.72
    67.9  867.67    77.6  861.56    87.4  856.91    97.2   855.4   175.4  855.08
   234.1  855.68   263.4  855.53   351.4  852.98   377.1  851.38   390.6  850.54
   400.4  850.89   410.1  851.62   419.9  852.04     459  852.72     547  855.49
   556.8  856.06   566.1  859.35   575.4  866.21   584.6  873.77   593.9     881
   603.2  887.02   621.7  896.92   658.8   917.9   668.1  922.88   686.7  931.99
#Mann= 3 , 0 , 0
       0      .1       0   377.1    .045       0   400.4      .1       0
Bank Sta=377.1,400.4
XS Rating Curve= 0 ,0
Exp/Cntr=0.3,0.1

Type RM Length L Ch R = 1 ,71      ,69.3,71,73.2
XS GIS Cut Line= 5
     1880805.255      514368.801     1880819.578       514436.51
     1881115.151      514676.093     1881228.432      514804.999
     1881449.787      514713.853
#Sta/Elev= 30
       0  884.21     8.6  879.63      26   871.3    51.9  860.38    60.6   857.3
    69.2  855.91      79  855.43   137.5  855.44   254.6  854.77   293.6  854.16
   332.6  854.16   342.4  853.58   359.4  849.99   361.9  849.42   371.6  849.23
   381.4  850.55   391.2  851.23   400.9   851.3   420.4  850.95   478.3  850.94
     545  852.46   640.4  855.45   707.5  856.23     717   858.5   726.6   865.5
   736.2  874.61   745.8  882.85   755.4  889.33   803.2  915.88   860.7  945.88
#Mann= 3 , 0 , 0
       0      .1       0   359.4    .045       0   381.4      .1       0
Bank Sta=359.4,381.4
XS Rating Curve= 0 ,0
Exp/Cntr=0.3,0.1

Chan Stop Cuts=-1
Use User Specified Reach Order=0
Composite Channel Slope=5